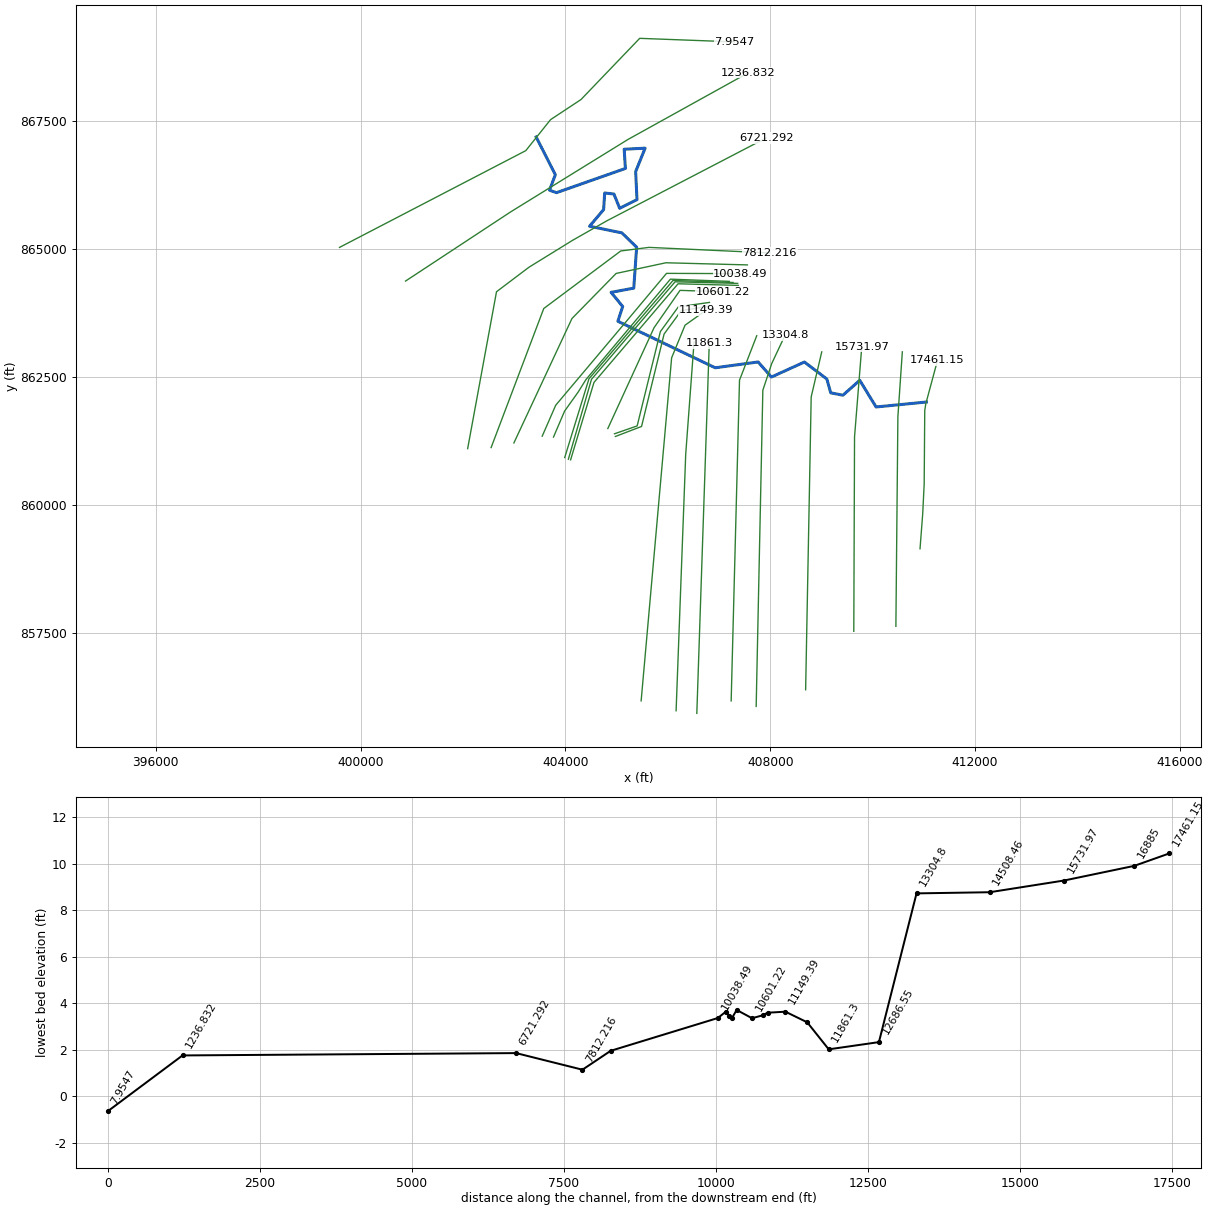
--- 7800_ras.prj (project) ---

Proj Title=7800
Current Plan=p01
Default Exp/Contr=0.3,0.1
English Units
Geom File=g01
Flow File=f01
Plan File=p01
Y Axis Title=Elevation
X Axis Title(PF)=Main Channel Distance
X Axis Title(XS)=Station
BEGIN DESCRIPTION:
RFD model 7800 exported to HEC-RAS
END DESCRIPTION:

--- 7800_ras.p01 (plan) ---

Plan Title=Plan 01
Program Version=4.10
Short Identifier=Plan 01
Geom File=g01
Flow File=f01
Subcritical Flow
Calc Critical at every XS
Secant Critical Depth

--- 7800_ras.f01 (steady flow) ---

Flow Title=Flow 01
Program Version=5.01
Number of Profiles= 6
Profile Names=10yr,25yr,50yr,100yr,100plus,500yr
River Rch & RM=7800,22,17461.15
 1980.81 3167.41 4283.42 5285.82  7717.3 9402.63
River Rch & RM=7800,22,   16885
 2084.13 3333.95 4510.02 5566.56 8127.17  9833.7
River Rch & RM=7800,22,15731.97
 2239.29 3584.48 4851.29 5989.77 8745.0710479.33
River Rch & RM=7800,22,14508.46
 2313.43 3704.66 5015.41 6193.75 9042.8710789.87
River Rch & RM=7800,22, 13304.8
 2333.23 3736.82 5059.38 6248.45 9122.7410873.15
River Rch & RM=7800,22,12686.55
  2350.7 3765.16 5098.11 6296.63 9193.07 10946.3
River Rch & RM=7800,22, 11861.3
 2381.17 3814.67 5165.83 6380.91 9316.1311074.35
River Rch & RM=7800,22,11507.55
 2393.24 3834.32 5192.75 6414.46 9365.11 11125.4
River Rch & RM=7800,22,11149.39
 2402.28 3849.05 5212.92 6439.59 9401.8111163.63
River Rch & RM=7800,22, 10857.3
 2406.43 3855.82  5222.2 6451.16  9418.711181.26
River Rch & RM=7800,22,10601.22
 2407.12 3856.94 5223.74 6453.09 9421.51 11184.2
River Rch & RM=7800,22,10347.44
 2429.94 3894.14 5274.73 6516.67 9514.3411280.95
River Rch & RM=7800,22,10272.06
 2431.31 3896.39 5277.81 6520.52 9519.96 11286.8
River Rch & RM=7800,22, 10171.8
 2432.46 3898.26 5280.38 6523.72 9524.6311291.68
River Rch & RM=7800,22,10038.49
  2433.6 3900.13 5282.95 6526.92 9529.3111296.56
River Rch & RM=7800,22,8276.032
 2498.68 4006.88 5429.87 6710.78 9797.7411577.97
River Rch & RM=7800,22,7812.216
 2556.76 4101.85 5560.28 6873.6610035.5411825.13
River Rch & RM=7800,22,6721.292
 2569.84 4123.33 5589.86  6910.710089.6311881.58
River Rch & RM=7800,22,1236.832
  3738.5 6054.72 8261.1410267.5314990.5916884.99
River Rch & RM=7800,22,  7.9547
 3855.14 6252.38 8538.8810621.3915507.2217414.69
Boundary for River Rch & Prof#=7800,22,1
Up Type= 0
Dn Type= 2
Boundary for River Rch & Prof#=7800,22,2
Up Type= 0
Dn Type= 2
Boundary for River Rch & Prof#=7800,22,2
Up Type= 0
Dn Type= 2
Boundary for River Rch & Prof#=7800,22,2
Up Type= 0
Dn Type= 2
Boundary for River Rch & Prof#=7800,22,2
Up Type= 0
Dn Type= 2
Boundary for River Rch & Prof#=7800,22,2
Up Type= 0
Dn Type= 2

--- 7800_ras.g01 (geometry) ---

Geom Title=7800
Program Version=4.10

River Reach=7800,22
Reach XY= 30
411049.084529728862005.002361745410065.751196414861908.474583954
409747.695640862862428.613472819409419.246262044862138.295540154
409180.204930693862184.749787003409105.284591228862454.486338958
408666.902816802862786.130833939408022.567371368862492.790615335
407762.736150116862787.519722849406925.236150146862673.630833954
405024.541705638863581.964167282405118.771865249863870.265368775
 404892.22226125864146.482685789405335.000039011864228.704908013
405390.994172275865027.904286429 405102.22226122865308.149352476
404471.666705638865437.038241357404746.549618214865761.932030395
404767.083372325866086.343796894404947.938559085866066.793360546
405060.000039011865787.593796909405397.916705668865957.177130252
405371.814853847866505.177130252 405557.37040934866961.843796894
 405147.88710463866940.927523419405171.693326026866565.634306163
403825.693326056866092.585695058403690.137770474866140.919028401
403803.471103847866443.696806177403429.116130054867180.425302669

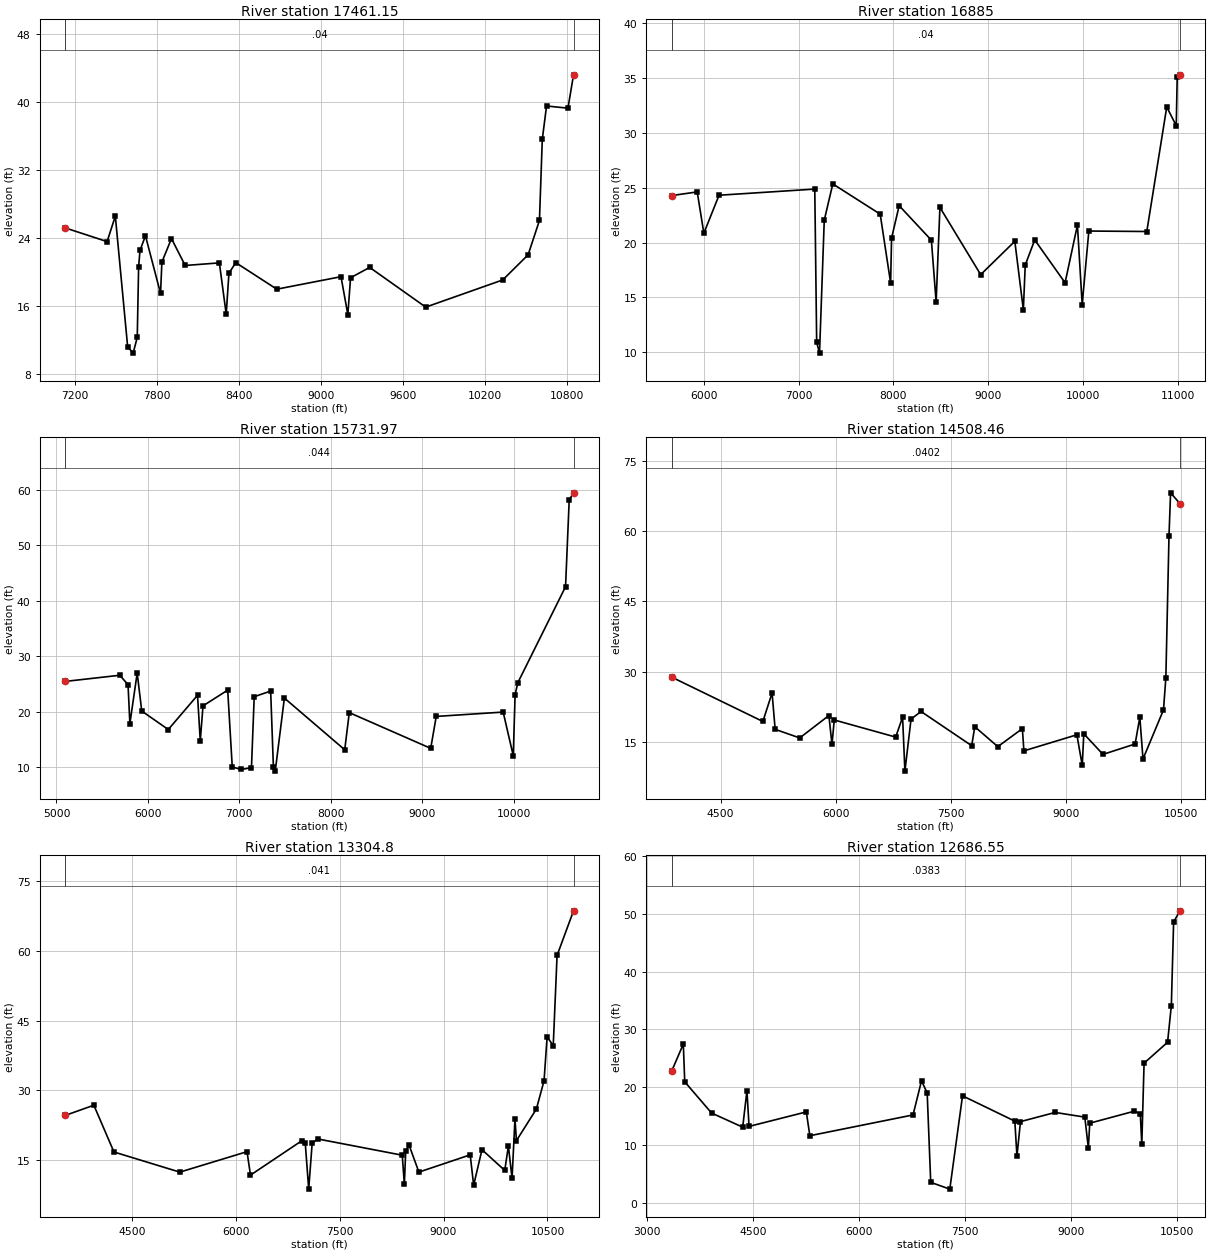
Type RM Length L Ch R = 1 ,17461.15,576.159100,576.159100,576.159100
XS GIS Cut Line= 6
410924.426999516859139.427124035410976.465504825859817.299556389
411005.649518311860405.787957177 411016.68956241861838.799265459
411036.876880527861969.587766156411267.083968042 862823.91869604
#Sta/Elev= 30
7127.27825.182987433.87723.570077494.05926.571637584.33211.199437624.454 10.4513
7654.52412.303097664.547 20.59677674.56922.535127714.65824.256767824.891 17.4753
7834.90621.163997905.016 23.92628005.173 20.76148255.47621.06817 8305.52 15.0439
8325.53819.849388375.58221.096818675.70117.973369145.73119.442739195.73514.98548
9215.73619.320669355.74520.533449765.824 15.862910329.6719.0638410515.11 22.0163
10598.1126.0626910618.8635.5930210649.9839.5225510806.7839.2676710847.5443.18877
#Mann= 3 , 0 , 0
7127.278    0.04       07127.278    0.04       010847.54    0.04       0
#XS Ineff= 2 , 0
       07896.221                       0
Bank Sta=7127.278,10847.54
Exp/Cntr=0.3,0.1

Type RM Length L Ch R = 1 ,   16885,1153.024900,1153.024900,1153.024900
XS GIS Cut Line= 3
410453.052489251857625.515975997410492.073518485861714.919840306
410578.879074097862984.451090321
#Sta/Elev= 30
5661.33624.292775930.833 24.62446000.83620.856036160.84324.323057170.88924.88322
 7190.89 10.90347220.891 9.914877270.89422.044477360.89825.35439 7860.9222.59624
7970.92516.317437980.92620.40596 8060.9323.370618400.94520.218628450.94714.56809
8490.94923.210478920.96917.077599280.98520.119619370.98913.87095 9390.99 17.9548
9490.99520.246649811.14716.33587 9941.4521.600089991.56714.3432510061.7321.05609
10673.1521.0125210883.6532.3737610983.88 30.6703 10993.935.1112911023.42 35.3098
#Mann= 3 , 0 , 0
5661.336    0.04       05661.336    0.04       011023.42    0.04       0
#XS Ineff= 2 , 0
       08015.526                       0
Bank Sta=5661.336,11023.42
Exp/Cntr=0.3,0.1

Type RM Length L Ch R = 1 ,15731.97,1223.506700,1223.506700,1223.506700
XS GIS Cut Line= 3
409631.283814698857527.748579726409645.719351828861324.294840321
409786.778379619863082.107340306
#Sta/Elev= 30
5095.55825.447515692.81326.561265782.814 24.85865802.81417.835085882.81526.95402
5932.81520.112076222.81716.78113 6542.8222.94965 6572.8214.74626 6602.8221.04444
6872.82223.879886922.82210.025687022.823 9.588237132.8249.9090397162.824 22.6926
7342.82523.713657372.8269.9818917392.8269.2845817492.826 22.44838152.83113.13075
8202.83219.826239093.48213.389169153.67519.142019886.02119.925219996.37512.05355
10016.4423.0706410046.5425.2241810568.21 42.513410608.3458.1678610655.5959.43116
#Mann= 3 , 0 , 0
5095.558   0.044       05095.558   0.044       010655.59   0.044       0
#XS Ineff= 2 , 0
       07668.453                       0
Bank Sta=5095.558,10655.59
Exp/Cntr=0.3,0.1

Type RM Length L Ch R = 1 ,14508.46,1203.659100,1203.659100,1203.659100
XS GIS Cut Line= 3
408690.858240724856387.228868097408799.365185201862105.544840336
409005.528379619862984.451090321
#Sta/Elev= 30
3863.21428.823085051.19919.368835171.22125.456185211.22817.689285531.28615.85727
5911.35420.637895951.361 14.49515981.367 19.68776781.51116.038836871.52720.29397
6901.5328.7798886981.54719.86905 7111.5721.500277771.68914.199727811.69618.24875
 8111.7514.002798431.80817.842078451.81113.101259141.93616.530419211.9489.981413
9231.95216.744369481.99712.351089900.41414.564939962.04320.2785410003.1311.36414
10270.1921.83741   1030128.6810210342.0959.0067810362.6368.1252310485.3265.81535
#Mann= 3 , 0 , 0
3863.214  0.0402       03863.214  0.0402       010485.32  0.0402       0
#XS Ineff= 2 , 0
       07704.549                       0
Bank Sta=3863.214,10485.32
Exp/Cntr=0.3,0.1

Type RM Length L Ch R = 1 , 13304.8,618.250700,618.250700,618.250700
XS GIS Cut Line= 4
407725.146435171856061.708034769407855.354768515862235.753173634
408028.965879619862756.586506978408289.382546276863309.971923649
#Sta/Elev= 30
3539.93124.598453953.31526.798854243.37916.726085193.59112.390886163.80616.79295
6213.81711.750156953.98219.140567003.99318.675957054.0048.7299277104.015 18.6193
7184.03319.534188404.30416.033518434.3119.7338028454.31617.004898504.32718.13461
8644.358 12.39379384.52216.110669434.5339.568323 9554.5617.22226 9883.2112.75736
9935.91517.987599988.61911.0618810030.7823.8293410051.8619.1730510339.9725.98013
10450.4932.0734910494.6941.4889510583.1139.6389410638.3759.0470510875.9568.65088
#Mann= 3 , 0 , 0
3539.931   0.041       03539.931   0.041       010875.95   0.041       0
#XS Ineff= 2 , 0
       07913.243                       0
Bank Sta=3539.931,10875.95
Exp/Cntr=0.3,0.1

Type RM Length L Ch R = 1 ,12686.55,825.252400,825.252400,825.252400
XS GIS Cut Line= 3
407236.865185171856170.214979202407399.625601858862431.065673649
407735.997129619863299.121229202
#Sta/Elev= 30
3344.39122.772923509.23127.476063529.23820.924943909.36715.510754349.51513.06558
4409.53519.383974439.54613.195615249.81915.705995299.836 11.58096760.32915.18338
 6880.3721.113096960.39718.975737010.4143.5036377280.5052.3249957460.56618.49875
8200.81614.105298230.826 8.054738280.84314.023298771.00915.61558 9191.1514.80462
9241.1679.4786199261.17413.755179890.414 15.8275 9976.2115.427739997.65910.07843
10029.83 24.157110362.29 27.776810415.9234.1494610448.0948.6418310538.31 50.5593
#Mann= 3 , 0 , 0
3344.391  0.0383       03344.391  0.0383       010538.31  0.0383       0
#XS Ineff= 2 , 0
       08520.361                       0
Bank Sta=3344.391,10538.31
Exp/Cntr=0.3,0.1

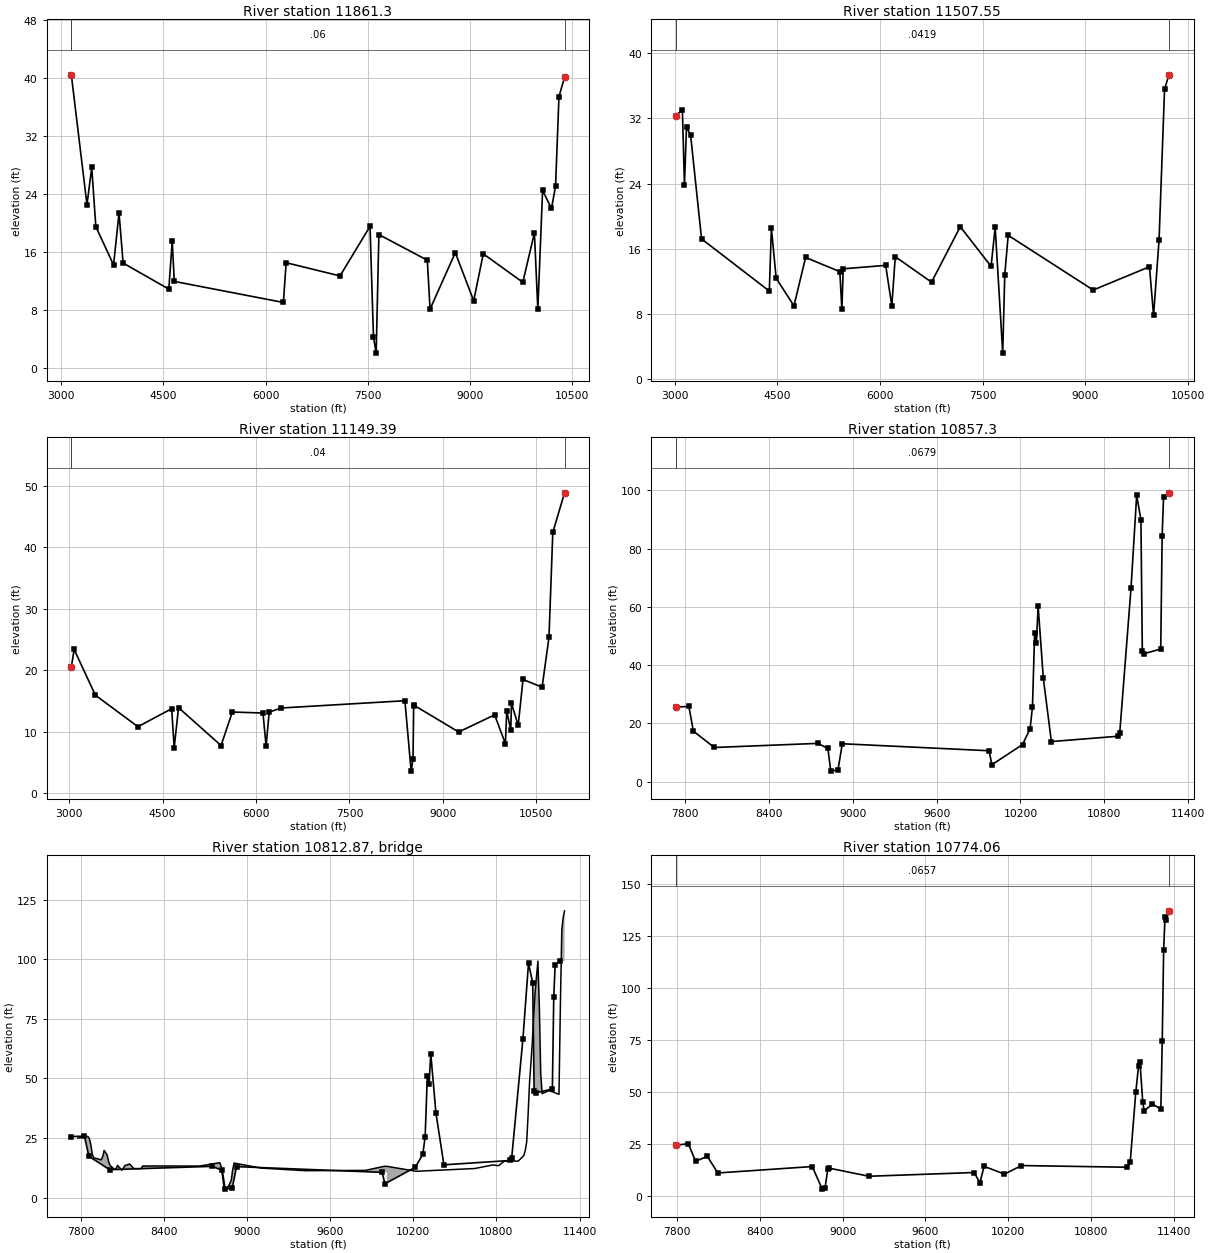
Type RM Length L Ch R = 1 , 11861.3,353.752300,353.752300,353.752300
XS GIS Cut Line= 2
406566.292268515855925.712664396406809.347824037863156.615442172
#Sta/Elev= 30
3149.93340.41129 3379.3522.483383449.38927.638253509.423 19.4642 3769.5714.18035
3849.61521.350133909.64914.445414580.02810.841924630.05617.495184660.07311.90802
6260.9769.0038856300.99914.488827091.44512.666537531.69419.506017581.7224.267873
7621.7452.0141257661.76718.372228372.16814.832548412.1918.084174  8782.415.87718
9052.5529.2356019192.63115.713389772.95911.788719943.05518.602219993.0838.067971
10063.1224.46443 10193.221.9694810253.2325.0336210303.2637.4045710384.9240.05841
#Mann= 3 , 0 , 0
3149.933    0.06       03149.933    0.06       010384.92    0.06       0
#XS Ineff= 2 , 0
       09738.449                       0
Bank Sta=3149.933,10384.92
Exp/Cntr=0.3,0.1

Type RM Length L Ch R = 1 ,11507.55,358.159500,358.159500,358.159500
XS GIS Cut Line= 3
406161.778379649855976.927942157406349.278379619860983.872386619
406512.472824067863178.316831052
#Sta/Elev= 30
3013.95132.306463112.09233.048983142.113 23.78553172.134  30.9193232.17629.93202
3392.28917.200184382.98210.796224413.004 18.55654483.05312.367544743.2358.988049
4913.35414.923455413.70413.182245443.7258.5706915463.73913.528736084.17413.95249
6174.2378.9634676224.272 15.01886754.64411.887047174.93818.698417625.25313.82906
7685.29618.614677795.3733.1780997825.39412.829777875.42917.638369118.54610.92381
 9940.8113.7831710000.987.803455 10081.217.0864110161.4235.5504310224.9137.34249
#Mann= 3 , 0 , 0
3013.951  0.0419       03013.951  0.0419       010224.91  0.0419       0
#XS Ineff= 2 , 0
       09681.175                       0
Bank Sta=3013.951,10224.91
Exp/Cntr=0.3,0.1

Type RM Length L Ch R = 1 ,11149.39,292.085400,292.085400,292.085400
XS GIS Cut Line= 4
405479.052685171856170.214979216406074.500536859  862868.5781845
406336.257546306863505.284423634406748.583935171863798.253173649
#Sta/Elev= 30
3034.86320.551053079.82423.415973421.16515.976464103.84710.859124645.97613.78259
4686.1347.447593 4756.4113.948345439.0917.7944765619.80113.244666111.73313.07988
 6161.937.7610756212.12813.228636402.87713.894178390.685 15.07878491.0793.634613
8521.1975.6072848531.23714.220818541.27614.316179254.0769.9952779831.45612.77951
10004.458.08929910026.0713.4243810090.9510.2875710101.7614.6702910209.8811.07541
10286.9518.5355310593.7217.2770910704.1225.3827810765.4642.4319210953.8648.87382
#Mann= 3 , 0 , 0
3034.863    0.04       03034.863    0.04       010953.86    0.04       0
#XS Ineff= 2 , 0
       09568.767        10150.97       0
Bank Sta=3034.863,10953.86
Exp/Cntr=0.3,0.1

Type RM Length L Ch R = 1 , 10857.3,83.240800,83.240800,83.240800
XS GIS Cut Line= 5
404976.798791349861332.673855826405487.215457976861527.986355826
405927.319624692863332.673855811406263.257124692 863791.00718917
406812.736291319863876.944689184
#Sta/Elev= 30
7733.24825.599397827.68625.805767859.80717.330198009.70711.712598750.16413.12091
8822.215 11.39068842.8023.5916858894.2674.0004268925.14612.995579975.03810.59345
9995.6255.79844310214.6112.7259410268.7418.1026310285.65 25.5689 10301.451.00891
 10313.847.5537110326.1960.3536410363.3935.5254810420.9813.7510410899.6715.58049
10909.7916.5468210990.7666.4132311031.2598.3327111061.6290.0120411071.7444.72365
11081.8643.8986811203.3245.5432211213.44  84.19511223.5697.6933511261.7699.18846
#Mann= 3 , 0 , 0
7733.248  0.0679       07733.248  0.0679       011261.76  0.0679       0
#XS Ineff= 2 , 0
       09493.695         10299.6       0
Bank Sta=7733.248,11261.76
Exp/Cntr=0.3,0.1

Type RM Length L Ch R = 3 ,10812.87,,,
BEGIN DESCRIPTION:
END DESCRIPTION:
Bridge Culvert--1,0,-1,-1, 0
Deck Dist Width WeirC Skew NumUp NumDn MinLoCord MaxHiCord MaxSubmerge Is_Ogee
30.629600,21.981600,2.6,0, 60, 60, , , 0.95, 0, 0,0,,
 7780.32 7852.71 7863.39 7874.07 7884.75 7895.43 7948.83 7959.51 7970.19 7991.55
 8002.23 8012.91 8044.95 8055.63 8066.31 8098.35 8119.71 8153.62 8183.79 8237.19
 8247.87 8660.18 8804.30 8814.59 8835.18 8855.77 8886.65 8896.94 8907.24 9102.83
 9421.95 9854.31 9989.99 9989.9910010.0110010.0110221.2910642.5210774.8710815.41
10855.9410957.2710997.8011007.9311018.0611028.2011038.3311058.5911068.7311078.86
11099.1311109.2611119.3911129.5211180.1911251.1211261.2511271.3811281.5211291.15
   24.99   25.67   24.78   22.20   18.16   16.71   15.83   17.19   19.79   17.89
   15.14   13.50   11.87   12.07   13.51   11.47   13.41   14.11   12.20   12.14
   13.27   13.25   14.65   12.97    4.23    3.56    7.16   11.59   14.49   12.38
   11.29   11.41   13.13   13.13   13.12   13.12   11.05   12.20   13.71   13.38
   15.26   15.31   17.66   19.82   23.24   34.66   47.80   64.75   76.68   86.25
   99.20   80.38   52.26   43.61   44.93   43.32   80.95  112.15  117.45  120.29
 -975.01 -974.33 -975.22 -977.80 -981.84 -983.29 -984.17 -982.81 -980.21 -982.11
 -984.86 -986.50 -988.13 -987.93 -986.49 -988.53 -986.59 -985.89 -987.80 -987.86
 -986.73 -986.75 -985.35 -987.03 -995.77 -996.44 -992.84 -988.41 -985.51 -987.62
 -988.71 -988.59 -986.87   10.63   10.62 -986.88 -988.95 -987.80 -986.29 -986.62
 -984.74 -984.69 -982.34 -980.18 -976.76 -965.34 -952.20 -935.25 -923.32 -913.75
 -900.80 -919.62 -947.74 -956.39 -955.07 -956.68 -919.05 -887.85 -882.55 -879.71
 7780.32 7852.71 7863.39 7874.07 7884.75 7895.43 7948.83 7959.51 7970.19 7991.55
 8002.23 8012.91 8044.95 8055.63 8066.31 8098.35 8119.71 8153.62 8183.79 8237.19
 8247.87 8660.18 8804.30 8814.59 8835.18 8855.77 8886.65 8896.94 8907.24 9102.83
 9421.95 9854.31 9989.99 9989.9910010.0110010.0110221.2910642.5210774.8710815.41
10855.9410957.2710997.8011007.9311018.0611028.2011038.3311058.5911068.7311078.86
11099.1311109.2611119.3911129.5211180.1911251.1211261.2511271.3811281.5211291.15
   24.99   25.67   24.78   22.20   18.16   16.71   15.83   17.19   19.79   17.89
   15.14   13.50   11.87   12.07   13.51   11.47   13.41   14.11   12.20   12.14
   13.27   13.25   14.65   12.97    4.23    3.56    7.16   11.59   14.49   12.38
   11.29   11.41   13.13   13.13   13.12   13.12   11.05   12.20   13.71   13.38
   15.26   15.31   17.66   19.82   23.24   34.66   47.80   64.75   76.68   86.25
   99.20   80.38   52.26   43.61   44.93   43.32   80.95  112.15  117.45  120.29
 -975.01 -974.33 -975.22 -977.80 -981.84 -983.29 -984.17 -982.81 -980.21 -982.11
 -984.86 -986.50 -988.13 -987.93 -986.49 -988.53 -986.59 -985.89 -987.80 -987.86
 -986.73 -986.75 -985.35 -987.03 -995.77 -996.44 -992.84 -988.41 -985.51 -987.62
 -988.71 -988.59 -986.87   10.63   10.62 -986.88 -988.95 -987.80 -986.29 -986.62
 -984.74 -984.69 -982.34 -980.18 -976.76 -965.34 -952.20 -935.25 -923.32 -913.75
 -900.80 -919.62 -947.74 -956.39 -955.07 -956.68 -919.05 -887.85 -882.55 -879.71
BR Coef=-1 , 0 , 0 ,, 0 ,,,0.8,0,1,0,
WSPro=,,,, 1 ,,,, 0 ,,,, 0 ,,,,-1 ,-1 ,-1 , 0 , 0 , 0 , 0 , 0
BC Design=,, 0 ,, 0 ,,,,,,

Type RM Length L Ch R = 1 ,10774.06,172.845800,172.845800,172.845800
XS GIS Cut Line= 5
404958.569624662 861384.75718914405401.277957976861538.403022468
405854.402957976863379.548855811406205.965457976863863.923855811
406812.736291319863949.861355811
#Sta/Elev= 30
7789.39224.555337880.879 25.31717933.80516.829318018.48619.225358095.12811.24022
8779.71814.326678851.8073.4782858872.4044.089304    8893 13.36868903.29913.52917
9191.6549.6589159953.73611.459779994.9296.53604810025.8214.4232910173.1810.68923
10296.7514.8087711064.7213.9846211084.9216.3830111125.32 49.954711145.5262.67187
11155.6264.5604511175.8245.4967911185.9241.0889711246.5244.2791711307.1141.98902
11317.2174.4999111327.31118.168111337.41134.315511347.51 132.62611365.43137.1314
#Mann= 3 , 0 , 0
7789.392  0.0657       07789.392  0.0657       011365.43  0.0657       0
#XS Ineff= 2 , 0
       0 9470.66        10342.02       0
Bank Sta=7789.392,11365.43
Exp/Cntr=0.3,0.1

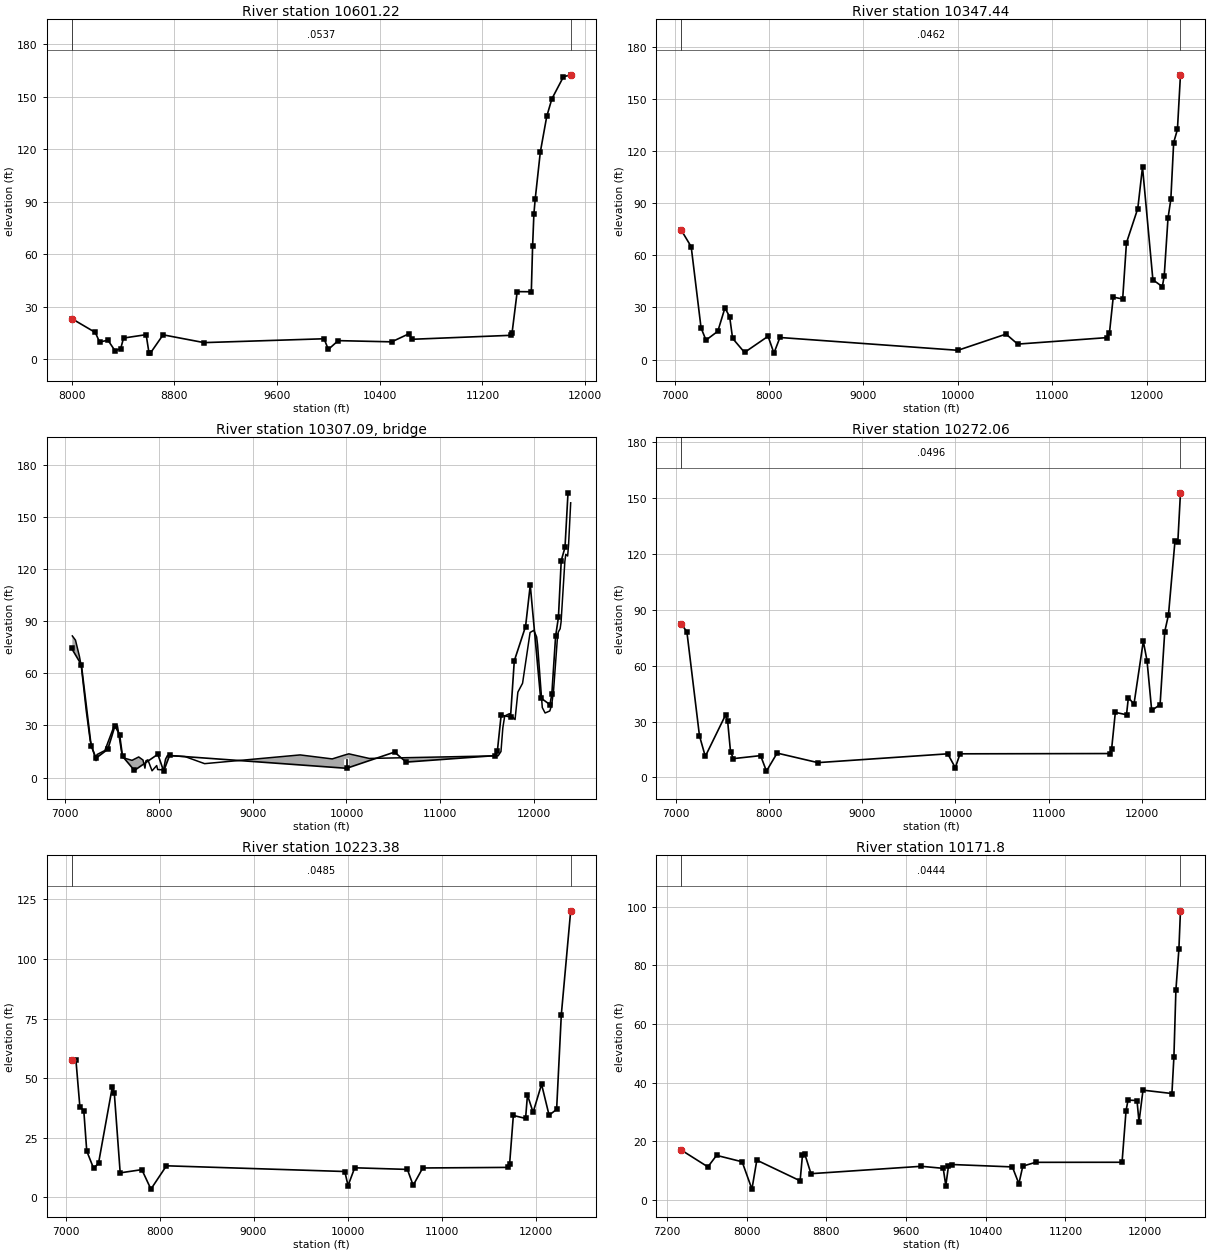
Type RM Length L Ch R = 1 ,10601.22,253.780600,253.780600,253.780600
XS GIS Cut Line= 4
404828.445046276861487.344608828405731.222824037863456.094608828
406238.167268485864185.261275515407071.500601828864157.483497724
#Sta/Elev= 30
7999.87723.128578184.31815.177678217.3229.748882 8283.3310.702538338.3364.662984
8382.3415.9716248404.34311.972298580.36313.913798602.3653.5726328613.3673.353258
8712.37813.823419031.4149.3652499966.518 11.57129999.5225.46300910076.5310.49964
10493.259.80742310627.2314.4109310651.5811.2709711420.8613.5414311430.8614.85261
11470.8838.5261311580.9438.4645411590.9564.5014511600.9682.9389411610.9691.32604
11650.98118.325711701.01138.717411741.03148.792211831.08161.414711887.62162.5403
#Mann= 3 , 0 , 0
7999.877  0.0537       07999.877  0.0537       011887.62  0.0537       0
#XS Ineff= 2 , 0
       09383.611         10408.3       0
Bank Sta=7999.877,11887.62
Exp/Cntr=0.3,0.1

Type RM Length L Ch R = 1 ,10347.44,75.379900,75.379900,75.379900
XS GIS Cut Line= 4
404101.798791349860875.642605811404557.947047323862387.552002296
406199.972824037864313.733497739 407377.05615738864282.483497739
#Sta/Elev= 30
7071.94374.313067175.72464.933977280.17618.255737332.40211.186337457.74516.28203
7533.09629.660197583.087  24.7197614.42312.217877740.8214.1058797990.45113.40582
8052.4083.7099888115.79312.7030410001.285.33681110511.7714.6605710635.098.900026
11577.4212.6161811607.4315.3249511647.4535.9196811747.4834.85376 11787.567.15473
11907.5486.8999211957.56110.7259 12067.6  45.89112167.6341.9592612187.64 48.1251
12227.6581.2987212257.6692.1566412287.67124.821912327.69 132.40212359.75163.8064
#Mann= 3 , 0 , 0
7071.943  0.0462       07071.943  0.0462       012359.75  0.0462       0
#XS Ineff= 2 , 0
       09188.078        10589.31       0
Bank Sta=7071.943,12359.75
Exp/Cntr=0.3,0.1

Type RM Length L Ch R = 3 ,10307.09,,,
BEGIN DESCRIPTION:
END DESCRIPTION:
Bridge Culvert--1,0,-1,-1, 0
Deck Dist Width WeirC Skew NumUp NumDn MinLoCord MaxHiCord MaxSubmerge Is_Ogee
26.535100,22.309700,2.6,0, 60, 60, , , 0.95, 0, 0,0,,
 7079.41 7113.20 7154.88 7175.72 7227.83 7269.51 7332.03 7342.45 7425.82 7519.60
 7550.86 7561.28 7613.38 7715.36 7786.49 7832.21 7853.05 7863.47 7884.32 7928.74
 7978.10 7988.52 8051.04 8071.88 8092.72 8280.29 8488.70 9505.95 9847.93 9974.90
 9974.9010025.1010025.1010242.5211615.5711645.5811665.5911685.6011735.6211795.64
11825.6611875.6811955.7111995.7212025.7412035.7412085.7612115.7712165.7912185.80
12205.8112245.8212255.8312275.8412285.8412325.8612335.8612355.8712365.8712388.30
   81.49   79.04   69.80   63.66   38.29   21.36    9.72   13.26   15.57   28.99
   30.44   29.36   11.51    9.92   11.87   10.10    5.42    9.65   10.21    3.89
    6.90    4.62    4.42   10.55   12.71   12.07    8.01   13.04   10.74   12.88
   12.88   13.66   13.66   11.01   12.53   14.97   28.64   35.44   36.76   33.40
   49.15   54.26   83.46   84.71   80.89   76.36   40.29   37.16   38.32   41.75
   50.05   79.51   83.66   85.62   89.46  124.10  128.42  127.47  133.99  158.06
 -918.51 -920.96 -930.20 -936.34 -961.71 -978.64 -990.28 -986.74 -984.43 -971.01
 -969.56 -970.64 -988.49 -990.08 -988.13 -989.90 -994.58 -990.35 -989.79 -996.11
 -993.10 -995.38 -995.58 -989.45 -987.29 -987.93 -991.99 -986.96 -989.26 -987.12
   10.38   11.16 -986.34 -988.99 -987.47 -985.03 -971.36 -964.56 -963.24 -966.60
 -950.85 -945.74 -916.54 -915.29 -919.11 -923.64 -959.71 -962.84 -961.68 -958.25
 -949.95 -920.49 -916.34 -914.38 -910.54 -875.90 -871.58 -872.53 -866.01 -841.94
 7079.41 7113.20 7154.88 7175.72 7227.83 7269.51 7332.03 7342.45 7425.82 7519.60
 7550.86 7561.28 7613.38 7715.36 7786.49 7832.21 7853.05 7863.47 7884.32 7928.74
 7978.10 7988.52 8051.04 8071.88 8092.72 8280.29 8488.70 9505.95 9847.93 9974.90
 9974.9010025.1010025.1010242.5211615.5711645.5811665.5911685.6011735.6211795.64
11825.6611875.6811955.7111995.7212025.7412035.7412085.7612115.7712165.7912185.80
12205.8112245.8212255.8312275.8412285.8412325.8612335.8612355.8712365.8712388.30
   81.49   79.04   69.80   63.66   38.29   21.36    9.72   13.26   15.57   28.99
   30.44   29.36   11.51    9.92   11.87   10.10    5.42    9.65   10.21    3.89
    6.90    4.62    4.42   10.55   12.71   12.07    8.01   13.04   10.74   12.88
   12.88   13.66   13.66   11.01   12.53   14.97   28.64   35.44   36.76   33.40
   49.15   54.26   83.46   84.71   80.89   76.36   40.29   37.16   38.32   41.75
   50.05   79.51   83.66   85.62   89.46  124.10  128.42  127.47  133.99  158.06
 -918.51 -920.96 -930.20 -936.34 -961.71 -978.64 -990.28 -986.74 -984.43 -971.01
 -969.56 -970.64 -988.49 -990.08 -988.13 -989.90 -994.58 -990.35 -989.79 -996.11
 -993.10 -995.38 -995.58 -989.45 -987.29 -987.93 -991.99 -986.96 -989.26 -987.12
   10.38   11.16 -986.34 -988.99 -987.47 -985.03 -971.36 -964.56 -963.24 -966.60
 -950.85 -945.74 -916.54 -915.29 -919.11 -923.64 -959.71 -962.84 -961.68 -958.25
 -949.95 -920.49 -916.34 -914.38 -910.54 -875.90 -871.58 -872.53 -866.01 -841.94
Pier Skew, UpSta & Num, DnSta & Num=  ,10000.00, 2 ,10000.00, 2 , 0 , 0 , 0 ,,
    3.00    3.00
 -986.73   13.27
    3.00    3.00
 -986.73   13.27
BR Coef=-1 , 0 , 0 ,, 0 ,,,0.8,0,1,0,
WSPro=,,,, 1 ,,,, 0 ,,,, 0 ,,,,-1 ,-1 ,-1 , 0 , 0 , 0 , 0 , 0
BC Design=,, 0 ,, 0 ,,,,,,

Type RM Length L Ch R = 1 ,10272.06,48.674800,48.674800,48.674800
XS GIS Cut Line= 4
404058.396013528 860888.66343914404509.784902424862448.993300274
406141.729346871864352.205105826407363.517541349864321.823161393
#Sta/Elev= 30
7059.93982.279187118.58678.317077253.91622.319917316.37711.281097534.987 33.6723
7555.80730.392867587.038 13.72437618.26810.091357909.74911.701067972.209 3.36721
8086.71913.060148523.9417.9368969917.241 12.66819998.077 5.1995410048.9712.66725
11654.7412.8135711674.75 15.154911714.7634.93822 11834.833.6758611854.8142.91293
11914.8239.3506212014.8673.1734212054.8762.6625312104.8835.9552712194.9139.12472
12244.9378.3527512284.9487.3698512354.96127.238912384.97126.2781 12413.5152.9284
#Mann= 3 , 0 , 0
7059.939  0.0496       07059.939  0.0496       0 12413.5  0.0496       0
#XS Ineff= 2 , 0
       09153.784         10656.2       0
Bank Sta=7059.939,12413.5
Exp/Cntr=0.3,0.1

Type RM Length L Ch R = 1 ,10223.38,51.584900,51.584900,51.584900
XS GIS Cut Line= 5
403986.781430215860921.215522468404459.871707976862457.673855811
 405434.26406911863599.166911379406100.496708006864378.246772498
407274.541846901864339.184272498
#Sta/Elev= 30
7065.09557.684457110.90857.626917152.76138.006777194.61536.344897226.00419.41517
7299.24812.136767351.56414.365067498.051 46.36617518.97743.798827581.75710.27594
 7811.9511.623797908.5853.4524098073.53313.238019970.85810.8407410005.26 4.90797
10076.0412.4042310636.2811.7199110697.835.04714110799.6512.3210311703.4412.56336
11723.4513.8635211763.4734.3511511893.5433.1011611913.5542.8964911973.5935.67012
12063.6447.4137312143.6834.4542212223.7336.8849412273.7576.6556612373.35120.1618
#Mann= 3 , 0 , 0
7065.095  0.0485       07065.095  0.0485       012373.35  0.0485       0
#XS Ineff= 2 , 0
       09137.223        10703.53       0
Bank Sta=7065.095,12373.35
Exp/Cntr=0.3,0.1

Type RM Length L Ch R = 1 , 10171.8,133.303300,133.303300,133.303300
XS GIS Cut Line= 6
403767.597402424861320.521078035403984.611291349861828.333578035
404249.368235767 862199.42732805404401.277957976862442.482883587
406050.583513558 864404.28843917407200.757124662864360.885661393
#Sta/Elev= 30
7346.02116.941157611.88811.228837698.88715.157197955.586 12.96848053.8913.640516
8102.99613.522798537.5776.4815888561.16215.270578584.74715.580058646.5438.908683
9753.25711.431099973.72210.731449999.7954.84488110025.8711.3608510065.0112.03273
10667.5911.2212910733.095.48496110772.3811.4836910900.9512.7812611768.55 12.8041
11808.5830.39815 11828.634.0054511918.6633.8699311938.6826.53645 11978.737.40453
12268.9136.2498212288.9248.7059712308.9471.5425712338.9685.4647512354.7398.57866
#Mann= 3 , 0 , 0
7346.021  0.0444       07346.021  0.0444       012354.73  0.0444       0
#XS Ineff= 2 , 0
       09127.471        10757.71       0
Bank Sta=7346.021,12354.73
Exp/Cntr=0.3,0.1

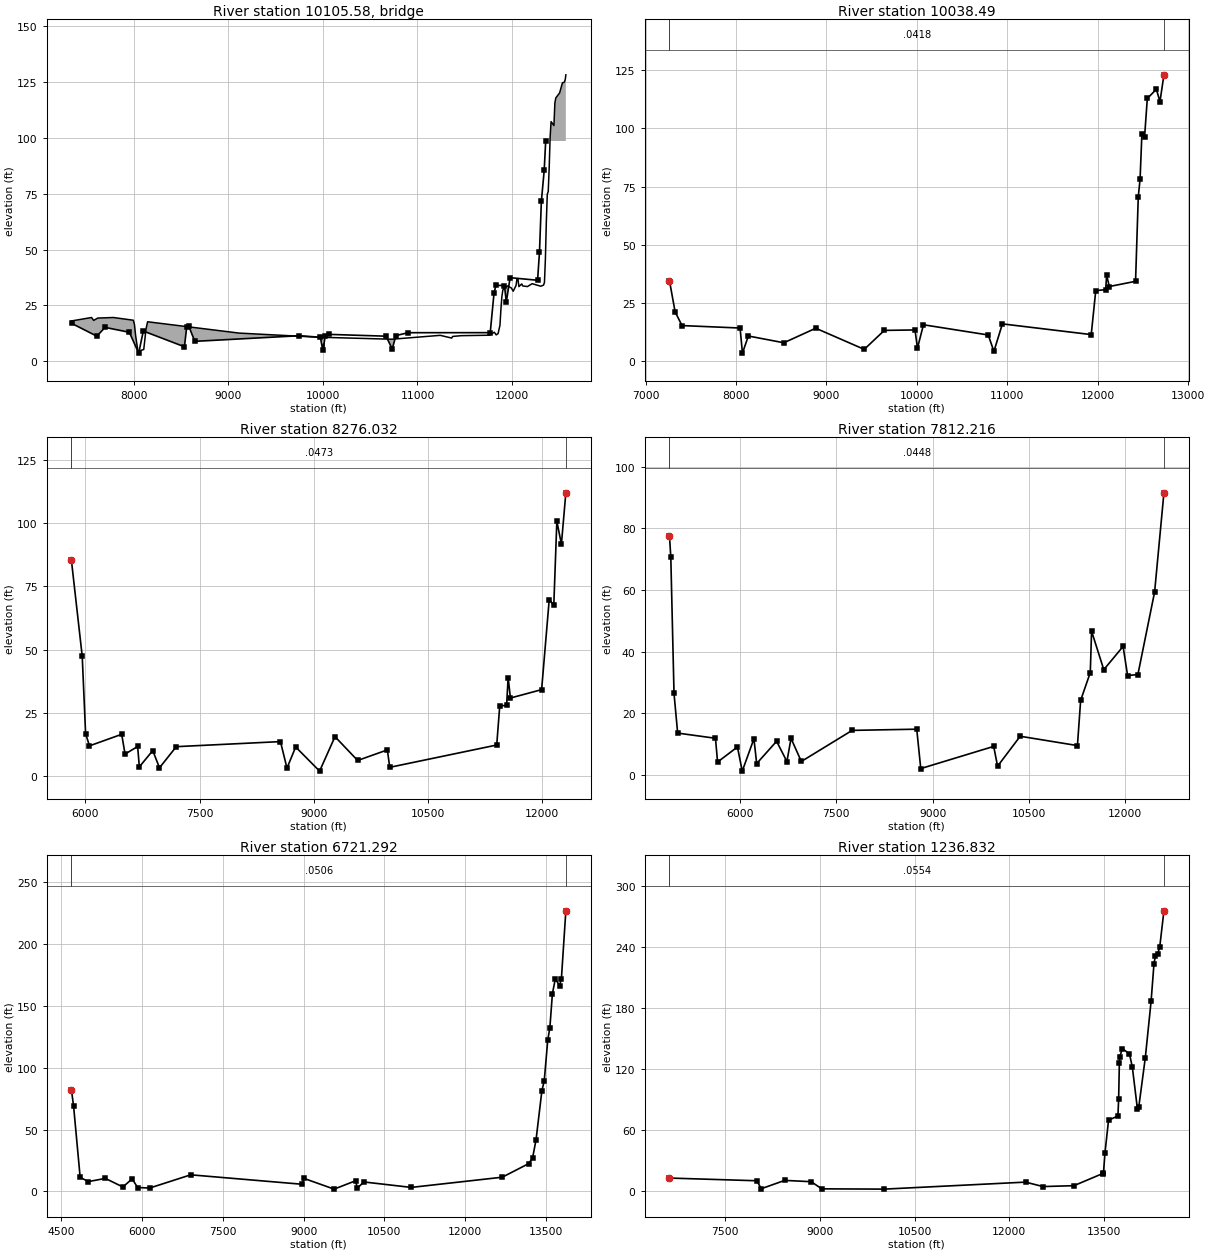
Type RM Length L Ch R = 3 ,10105.58,,,
BEGIN DESCRIPTION:
END DESCRIPTION:
Bridge Culvert--1,0,-1,-1, 0
Deck Dist Width WeirC Skew NumUp NumDn MinLoCord MaxHiCord MaxSubmerge Is_Ogee
49.591300,34.120700,2.6,0, 60, 60, , , 0.95, 0, 0,0,,
 7342.95 7556.29 7578.23 7622.10 7786.61 7997.11 8009.37 8021.63 8046.15 8107.45
 8131.96 8148.24 9114.24 9980.48 9980.4810019.5210019.5210731.3211240.2211361.47
11371.4711461.4911761.5311811.5411831.5411851.5511871.5511881.5511891.5511901.55
11911.5611951.5611991.5712011.5712041.5812051.5812061.5812071.5812101.5912111.59
12161.6012211.6012301.6212331.6212341.6212351.6312361.6312371.6312381.6312391.63
12401.6312411.6312441.6412451.6412461.6412501.6512531.6512551.6612561.6612567.63
   18.04   19.58   18.29   19.34   19.58   18.37   16.46   11.52    4.49    5.26
   14.56   17.68   12.61   10.70   10.70   10.69   10.69    9.86   11.60   10.38
   11.11   11.45   11.66   13.01   11.81   12.36   16.13   23.26   28.81   31.84
   32.52   33.74   32.80   31.35   33.93   36.99   36.88   33.41   34.61   33.72
   33.43   34.72   33.59   34.05   35.26   45.84   62.68   74.78   76.02   86.62
  100.41  107.25  105.49  115.56  117.87  120.09  124.62  124.91  126.12  128.19
 -981.96 -980.42 -981.71 -980.66 -980.42 -981.63 -983.54 -988.48 -995.51 -994.74
 -985.44 -982.32 -987.39 -989.30    8.20    8.19 -989.31 -990.14 -988.40 -989.62
 -988.89 -988.55 -988.34 -986.99 -988.19 -987.64 -983.87 -976.74 -971.19 -968.16
 -967.48 -966.26 -967.20 -968.65 -966.07 -963.01 -963.12 -966.59 -965.39 -966.28
 -966.57 -965.28 -966.41 -965.95 -964.74 -954.16 -937.32 -925.22 -923.98 -913.38
 -899.59 -892.75 -894.51 -884.44 -882.13 -879.91 -875.38 -875.09 -873.88 -871.81
 7342.95 7556.29 7578.23 7622.10 7786.61 7997.11 8009.37 8021.63 8046.15 8107.45
 8131.96 8148.24 9114.24 9980.48 9980.4810019.5210019.5210731.3211240.2211361.47
11371.4711461.4911761.5311811.5411831.5411851.5511871.5511881.5511891.5511901.55
11911.5611951.5611991.5712011.5712041.5812051.5812061.5812071.5812101.5912111.59
12161.6012211.6012301.6212331.6212341.6212351.6312361.6312371.6312381.6312391.63
12401.6312411.6312441.6412451.6412461.6412501.6512531.6512551.6612561.6612567.63
   18.04   19.58   18.29   19.34   19.58   18.37   16.46   11.52    4.49    5.26
   14.56   17.68   12.61   10.70   10.70   10.69   10.69    9.86   11.60   10.38
   11.11   11.45   11.66   13.01   11.81   12.36   16.13   23.26   28.81   31.84
   32.52   33.74   32.80   31.35   33.93   36.99   36.88   33.41   34.61   33.72
   33.43   34.72   33.59   34.05   35.26   45.84   62.68   74.78   76.02   86.62
  100.41  107.25  105.49  115.56  117.87  120.09  124.62  124.91  126.12  128.19
 -981.96 -980.42 -981.71 -980.66 -980.42 -981.63 -983.54 -988.48 -995.51 -994.74
 -985.44 -982.32 -987.39 -989.30    8.20    8.19 -989.31 -990.14 -988.40 -989.62
 -988.89 -988.55 -988.34 -986.99 -988.19 -987.64 -983.87 -976.74 -971.19 -968.16
 -967.48 -966.26 -967.20 -968.65 -966.07 -963.01 -963.12 -966.59 -965.39 -966.28
 -966.57 -965.28 -966.41 -965.95 -964.74 -954.16 -937.32 -925.22 -923.98 -913.38
 -899.59 -892.75 -894.51 -884.44 -882.13 -879.91 -875.38 -875.09 -873.88 -871.81
Pier Skew, UpSta & Num, DnSta & Num=  ,9993.16, 2 ,9993.16, 2 , 0 , 0 , 0 ,,
    2.00    2.00
 -989.32   10.68
    2.00    2.00
 -989.32   10.68
Pier Skew, UpSta & Num, DnSta & Num=  ,10006.84, 2 ,10006.84, 2 , 0 , 0 , 0 ,,
    2.00    2.00
 -989.32   10.68
    2.00    2.00
 -989.32   10.68
BR Coef=-1 , 0 , 0 ,, 0 ,,,0.8,0,1,0,
WSPro=,,,, 1 ,,,, 0 ,,,, 0 ,,,,-1 ,-1 ,-1 , 0 , 0 , 0 , 0 , 0
BC Design=,, 0 ,, 0 ,,,,,,

Type RM Length L Ch R = 1 ,10038.49,1762.462400,1762.462400,1762.462400
XS GIS Cut Line= 5
403547.195046276861338.039053291403811.083935171861942.205719918
405228.100874662 863625.20857805405974.628652424864517.135661393
407418.722824067864511.650164381
#Sta/Elev= 30
7264.74934.497527326.90721.140677403.293 15.21088045.33814.152778071.4833.362617
8136.84510.726158529.0197.8146168881.97514.063619417.9464.9816979640.17813.13772
9979.58113.3301810006.215.48212810072.7415.5546310789.2611.1622710851.584.107599
10945.4115.9315811927.6211.3322511977.6230.2515312087.6230.6378312097.6236.89349
12127.6232.0020712417.6334.2355912447.6370.5852112467.6378.1351812487.6397.44884
12517.6396.4392312547.63112.849112647.63116.803412687.63111.480612731.35123.0149
#Mann= 3 , 0 , 0
7264.749  0.0418       07264.749  0.0418       012731.35  0.0418       0
#XS Ineff= 2 , 0
       09086.632         10894.5       0
Bank Sta=7264.749,12731.35
Exp/Cntr=0.3,0.1

Type RM Length L Ch R = 1 ,8276.032,463.815400,463.815400,463.815400
XS GIS Cut Line= 5
402994.397013873861205.854085088404127.910743386863635.012698263
404990.771435201864515.701090306 405962.99365744864724.034423634
407553.271435171864682.367756978
#Sta/Elev= 30
5815.07485.436355957.588 47.35336001.72916.780276052.98611.950816476.23916.52089
 6520.388.6929176685.90711.700016707.977 3.623836884.53910.08641 6972.823.255792
7193.523 11.62738562.96913.632888648.7033.1432268763.01411.502719077.3721.949989
 9279.6515.588199577.4866.1635919968.16910.35428 9998.853.45395211405.1612.27498
11445.1727.81845 11535.227.9294711555.2138.9546511585.22 30.868211995.36 34.1886
12095.3969.8421412155.4167.5672212195.43100.823712255.4591.7556612313.74112.0502
#Mann= 3 , 0 , 0
5815.074  0.0473       05815.074  0.0473       012313.74  0.0473       0
#XS Ineff= 2 , 0
       0  8840.7        10415.68       0
Bank Sta=5815.074,12313.74
Exp/Cntr=0.3,0.1

Type RM Length L Ch R = 1 ,7812.216,1090.924100,1090.924100,1090.924100
XS GIS Cut Line= 5
402549.952569455861115.576307297403577.730347186863830.854085073
405081.917268485 864954.93720144405633.132546335865024.381645873
407989.903379679 864915.87470144
#Sta/Elev= 30
4904.00677.671354924.77570.600354974.76126.371435031.25713.499315619.781 11.8154
5652.7174.0921445961.9388.9886966036.7851.1367126218.556 11.65696261.3253.594273
6571.40510.842316731.7914.2537476795.94511.781226956.3314.2772617747.56914.37824
8752.654 14.76898815.0731.9629589950.2559.17230810010.732.73672710362.6612.46853
 11253.69.43724111303.6624.1379611453.8233.1707611473.84 46.607211664.0434.10955
11964.3641.6608712034.4332.20026 12194.632.5233612454.8859.3494712599.9391.57987
#Mann= 3 , 0 , 0
4904.006  0.0448       04904.006  0.0448       012599.93  0.0448       0
#XS Ineff= 2 , 0
       08697.316        10219.48       0
Bank Sta=4904.006,12599.93
Exp/Cntr=0.3,0.1

Type RM Length L Ch R = 1 ,6721.292,5484.460600,5484.460600,5484.460600
XS GIS Cut Line= 6
402091.619236082861094.742973968402655.049252212864158.480319723
403289.870453358864637.708089188404146.674212933865166.164053276
404810.736712933865543.768219963407918.175808549867160.208622262
#Sta/Elev= 30
4686.386   82.234727.31868.86506 4849.33 11.34435001.8457.9334085317.04410.51206
 5642.413.5968545815.26110.133335916.9383.1504066140.6272.7367446903.20413.40572
8978.8965.7554759002.39410.56784 9566.351.8518989969.7558.6884269992.7632.454826
 10119.37.63559810998.563.24177112688.7711.4710313179.0222.4240413252.1726.96493
13317.1841.8133413425.5381.3962413468.8689.2697613533.87122.093413573.55132.2843
13620.55159.7301   13675171.6593 13753.9166.191413787.72171.7811 13870.2226.5875
#Mann= 3 , 0 , 0
4686.386  0.0506       04686.386  0.0506       0 13870.2  0.0506       0
#XS Ineff= 2 , 0
       09068.048                       0
Bank Sta=4686.386,13870.2
Exp/Cntr=0.3,0.1

Type RM Length L Ch R = 1 ,1236.832,1228.877000,1228.877000,1228.877000
XS GIS Cut Line= 4
400878.861594975864366.793317348402929.660324126  865716.5112755
405223.063101918867132.309886619407572.855641216868434.768555015
#Sta/Elev= 30
6614.15512.645927998.2189.9850468070.0472.1650318441.161 10.35168860.1619.057233
9027.7612.04183810018.211.75129912258.328.65303412533.234.27619213024.365.140495
13482.0817.1236413493.1317.87792   1351637.0277113573.1769.54783 13721.8 73.7594
13733.2390.0346813744.67125.805913750.24131.769313791.49139.965713904.74134.9502
13950.47121.7141 14030.580.9403814053.3782.9543514156.27131.217214247.74186.6662
14293.47223.606814316.34231.274114350.64232.835614384.94240.176814451.09275.5827
#Mann= 3 , 0 , 0
6614.155  0.0554       06614.155  0.0554       014451.09  0.0554       0
#XS Ineff= 2 , 0
       09051.462        12700.76       0
Bank Sta=6614.155,14451.09
Exp/Cntr=0.3,0.1

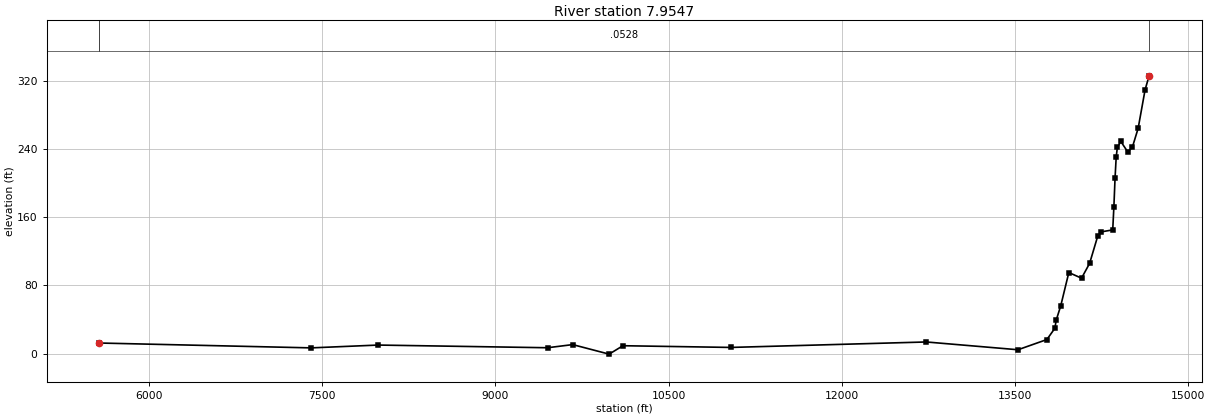
Type RM Length L Ch R = 1 ,  7.9547,0.000000,0.000000,0.000000
XS GIS Cut Line= 6
 399589.77260226865024.107564434403226.535324037866913.125858843
403710.476296514867518.594608843404305.094351828867911.389747739
405450.851996958869106.240348637407299.810330302869036.795904189
#Sta/Elev= 30
  5568.512.379877404.9426.680681 7984.759.9880569451.5246.8389759669.45310.51905
9984.926-0.6516210104.719.20848911039.187.20366712732.1613.61165 13525.84.488857
13775.9716.4527313846.0229.8297313856.0338.8449213896.06 55.975913966.1195.08127
14076.1988.4358214146.24105.831914216.28137.721614246.31142.789514346.38145.0777
14356.38 172.05714366.39205.5822 14376.4230.5309 14386.4241.870214416.43248.8652
14476.47236.5549 14516.5 242.08214566.53264.284114626.57309.408814661.41325.8371
#Mann= 3 , 0 , 0
  5568.5  0.0528       0  5568.5  0.0528       014661.41  0.0528       0
#XS Ineff= 2 , 0
       08089.667        12800.42       0
Bank Sta=5568.5,14661.41
Exp/Cntr=0.3,0.1